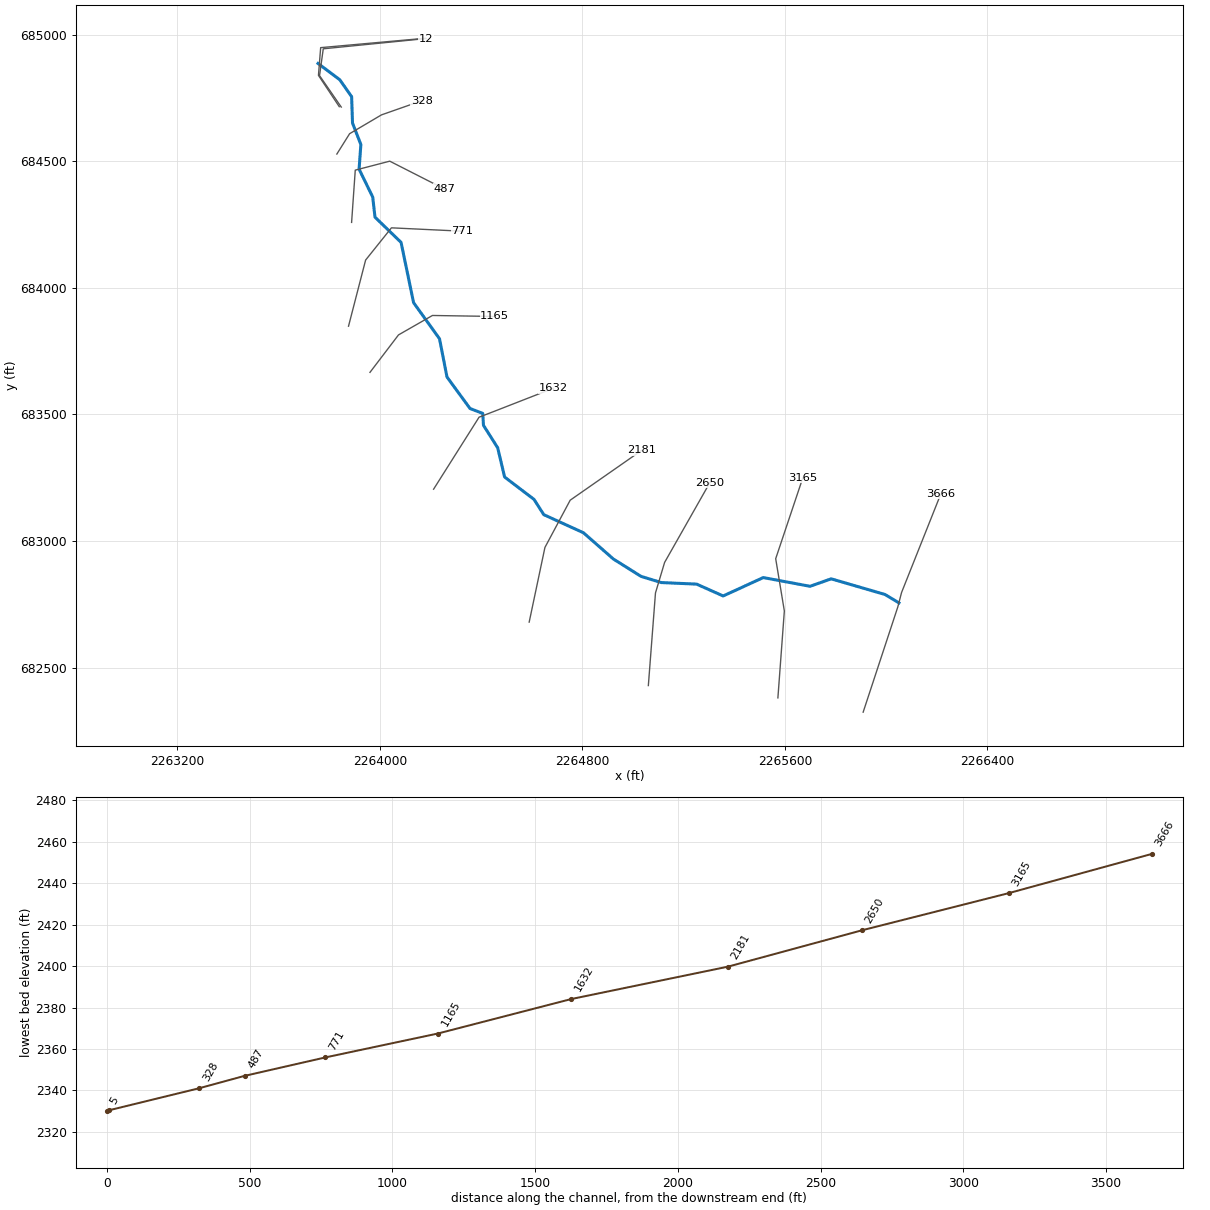
--- LAURLRN2T1.prj (project) ---

Proj Title=LAURLRN2T1
Current Plan=p01
Default Exp/Contr=0,0
English Units
Geom File=g01
Flow File=f01
Plan File=p01
BEGIN DESCRIPTION:
----------MODEL BY WOOD PLC 2022----------
AFH study
Randolph County, WV
HEC-RAS Version: RAS 6.2
Vertical Datum: NAVD88
Projection: NAD 1983 StatePlane West Virginia S FIPS 4702 (US Feet)
Terrain: 1-meter LIDAR (FEMA Region III 3DEP collected 2016-2018)
Land Use: 2019 NLCD
Hydrologic Method:
WV SIR2010-5033 regression equations
Additional Model Notes:
Dominant flow path issue; LAURLRN2T1 has a higher DA than LAURELRN2 at confluence
END DESCRIPTION:
DSS Export Rating Curves= 0
DSS Export Rating Curve Sorted= 0
DSS Export Volume Flow Curves= 0
DXF OffsetX= 0
DXF OffsetY= 0
DXF ScaleX= 0
DXF ScaleY= 0

--- LAURLRN2T1.p01 (plan) ---

Plan Title=Floodplain
Program Version=6.20
Short Identifier=Floodplain
Geom File=g01
Flow File=f01
Subcritical Flow
K Sum by GR= 0
Std Step Tol= 0.01
Critical Tol= 0.01
Num of Std Step Trials= 20
Max Error Tol= 0.3
Flow Tol Ratio= 0.001
Split Flow NTrial= 30
Split Flow Tol= 0.02
Split Flow Ratio= 0.02
Log Output Level= 0
Friction Slope Method= 1
Unsteady Friction Slope Method= 2
Unsteady Bridges Friction Slope Method= 1
Parabolic Critical Depth
Global Vel Dist= 0 , 0 , 0
Global Log Level= 0
CheckData=True
Encroach Param=-1 ,0,0, 0
Mapping Interval=1HOUR
Computation Time Step Use Courant=        0
Computation Time Step Use Time Series=    0
Computation Time Step Count To Double=0
Computation Time Step Max Doubling=0
Computation Time Step Max Halving=0
Computation Time Step Residence Courant=0
Run HTab= 0
Run UNet= 0
Run Sediment= 0
Run PostProcess= 0
Run WQNet= 0
Run RASMapper=-1
UNET Theta= 0
UNET Theta Warmup= 0
UNET ZTol= 0
UNET ZSATol= 0
UNET MxIter= 0
UNET Max Iter WO Improvement= 0
UNET MaxInSteps= 0
UNET DtIC= 0
UNET DtMin= 0
UNET MaxCRTS= 0
UNET WFStab= 0
UNET SFStab= 0
UNET WFX= 1
UNET SFX= 1
UNET Gravity=32.174
UNET 1D Methodology=Finite Difference
UNET DSS MLevel= 1
UNET Pardiso=0
UNET DZMax Abort= 0
UNET Use Existing IB Tables= 0
UNET Froude Reduction=False
UNET Froude Limit= 0
UNET Froude Power= 0
UNET D1 Cores= 0
UNET WindReference=Eulerian
UNET WindDragFormulation=Hsu (1988)
UNET D2 Coriolis=0
UNET D2 Cores= 0
UNET D2 Theta= 1
UNET D2 Theta Warmup= 1
UNET D2 Z Tol= 0.01
UNET D2 Volume Tol= 0.01
UNET D2 Max Iterations= 20
UNET D2 Equation= 0
UNET D2 RampUpFraction=0.1
UNET D2 TimeSlices= 1
UNET D2 Turbulence Formulation=Non-Conservative (original)
UNET D2 Eddy Viscosity=0.3
UNET D2 Transverse Eddy Viscosity=0.1
UNET D2 Smagorinsky Mixing=0
UNET D2 BCVolumeCheck=0
UNET D2 Cores=0
UNET D2 SolverType=PARDISO (Direct)
UNET D2 Minimum Iterations= 2147483647
UNET D2 Maximum Iterations= 2147483647
UNET D2 Restart Number= 10
UNET D2 Relaxation Coeff=1.3
UNET D2 SOR Precondition Iterations= 10
UNET D2 ILUT Maximum Fill= 8
UNET D2 ILUT Tolerance=1E-08
UNET D1D2 MaxIter= 0
UNET D1D2 ZTol=0.01
UNET D1D2 QTol=0.1
UNET D1D2 MinQTol=1
Write IC File= 0
Write IC File at Fixed DateTime=0
Write IC File at Sim End=0
Echo Input=False
Echo Parameters=False
Echo Output=False
Write Detailed= 0
HDF Write Warmup=0
HDF Write Time Slices=0
HDF Flush=0
HDF Compression= 1
HDF Chunk Size= 1
HDF Spatial Parts= 1
HDF Use Max Rows=0
HDF Fixed Rows= 1
Calibration Method= 0
Calibration Iterations= 20
Calibration Max Change=0.05
Calibration Tolerance=0.2
Calibration Maximum=1.5
Calibration Minimum=0.5
Calibration Optimization Method= 1
WQ AD Non Conservative
WQ ULTIMATE=-1
WQ Max Comp Step=1HOUR
WQ Output Interval=15MIN
WQ Output Selected Increments= 0
WQ Output face flow=0
WQ Output face velocity=0
WQ Output face area=0
WQ Output face dispersion=0
WQ Output cell volume=0
WQ Output cell surface area=0
WQ Output cell continuity=0
WQ Output cumulative cell continuity=0
WQ Output face conc=0
WQ Output face dconc_dx=0
WQ Output face courant=0
WQ Output face peclet=0
WQ Output face adv mass=0
WQ Output face disp mass=0
WQ Output cell mass=0
WQ Output cell source sink temp=0
WQ Output nsm pathways=0
WQ Output nsm derived pathways=0
WQ Create Restart=0
WQ Fixed Restart=0
WQ System Summary=0
WQ Write To DSS=0
Sorting and Armoring Iterations= 10
XS Update Threshold= 0.02
Bed Roughness Predictor= 0
Hydraulics Update Threshold= 0.02
Energy Slope Method= 1
Volume Change Method= 1
Sediment Retention Method= 0
Sediment TS Multiplier= 1
Warm Up Method= 0
XS Weighting Method= 0
Number of US Weighted Cross Sections= 1
Number of DS Weighted Cross Sections= 1
Upstream XS Weight=0
Main XS Weight=1
Downstream XS Weight=0
Number of DS XS's Weighted with US Boundary= 1
Upstream Boundary Weight= 1
Weight of XSs Associated with US Boundary= 0
Number of US XS's Weighted with DS Boundary= 1
Downstream Boundary Weight= 0.5
Weight of XSs Associated with DS Boundary= 0.5
Percentile Method= 0
Sediment Output Level= 3
Mass or Volume Output= 0
Output Increment Type= 1
Profile and TS Output Increment= 1
Transport Output Increment 1
XS Output Flag= 0
XS Output Increment= 10
Read HDF5 Sediment Hotstart= 0
Sediment Hotstart Type= 0
Write Gradation File= 0
Read Gradation Hotstart= 0
Write HDF5 File= 1
Write Binary Output= 1
Write DSS Sediment File= 0
DSS Sediment Output Type= 1
SV Curve= 0
Specific Gage Flag= 0
Subcell Erosion Methods= 0
Subcell Deposition Methods= 0
Advection Scheme= 1
Matrix Solver= 0
Implicit Weighting Factor= 1
Maximum Outer Loop Convergence Iterations= 5
Convergence Maximum Absolute= 0.001
Convergence RMSE= 0.0001
Grain Fractions Max Abs Error= 0.001
Max Subgrid Regions= 1
Max Subgrid Length Scale= 3.402823E+38
Initial Layer Thickness= 3.402823E+38
Min Layer Thickness= 3.402823E+38
Max Layer Thickness= 3.402823E+38
Number of Layers= 5

--- LAURLRN2T1.f01 (steady flow) ---

Flow Title=Flow
Program Version=6.20
Number of Profiles= 1
Profile Names=P100yr
River Rch & RM=LAURLRN2T1,Main            ,3666
     364
Boundary for River Rch & Prof#=LAURLRN2T1,Main            , 1
Up Type= 0
Dn Type= 3
Dn Slope=0.04
DSS Import GetInterval= 0
DSS Import GetPeak= 0
DSS Import FillOption= 0

--- LAURLRN2T1.g01 (geometry) ---

Geom Title=Geometry
Program Version=6.20

River Reach=LAURLRN2T1      ,Main
Reach XY= 30
     2266050.661      682755.574     2265995.872      682788.646
     2265782.866      682850.626     2265699.532      682821.112
     2265514.635        682855.6     2265356.216      682782.918
     2265251.295      682829.708     2265111.859      682835.869
     2265031.997      682860.174     2264922.623      682928.751
     2264804.083      683032.646     2264647.472      683104.111
     2264608.748      683164.536     2264492.718       683252.83
     2264465.297      683368.328       2264409.2      683457.121
     2264406.257       683504.18     2264356.025      683523.526
     2264264.998      683648.044     2264235.484      683799.085
     2264133.066       683941.66     2264083.587      684179.893
     2263980.521      684279.534     2263971.595      684358.981
     2263917.776      684469.224      2263924.72      684566.446
     2263891.734      684651.516     2263888.262      684755.682
     2263841.387      684822.522     2263755.435       684886.85

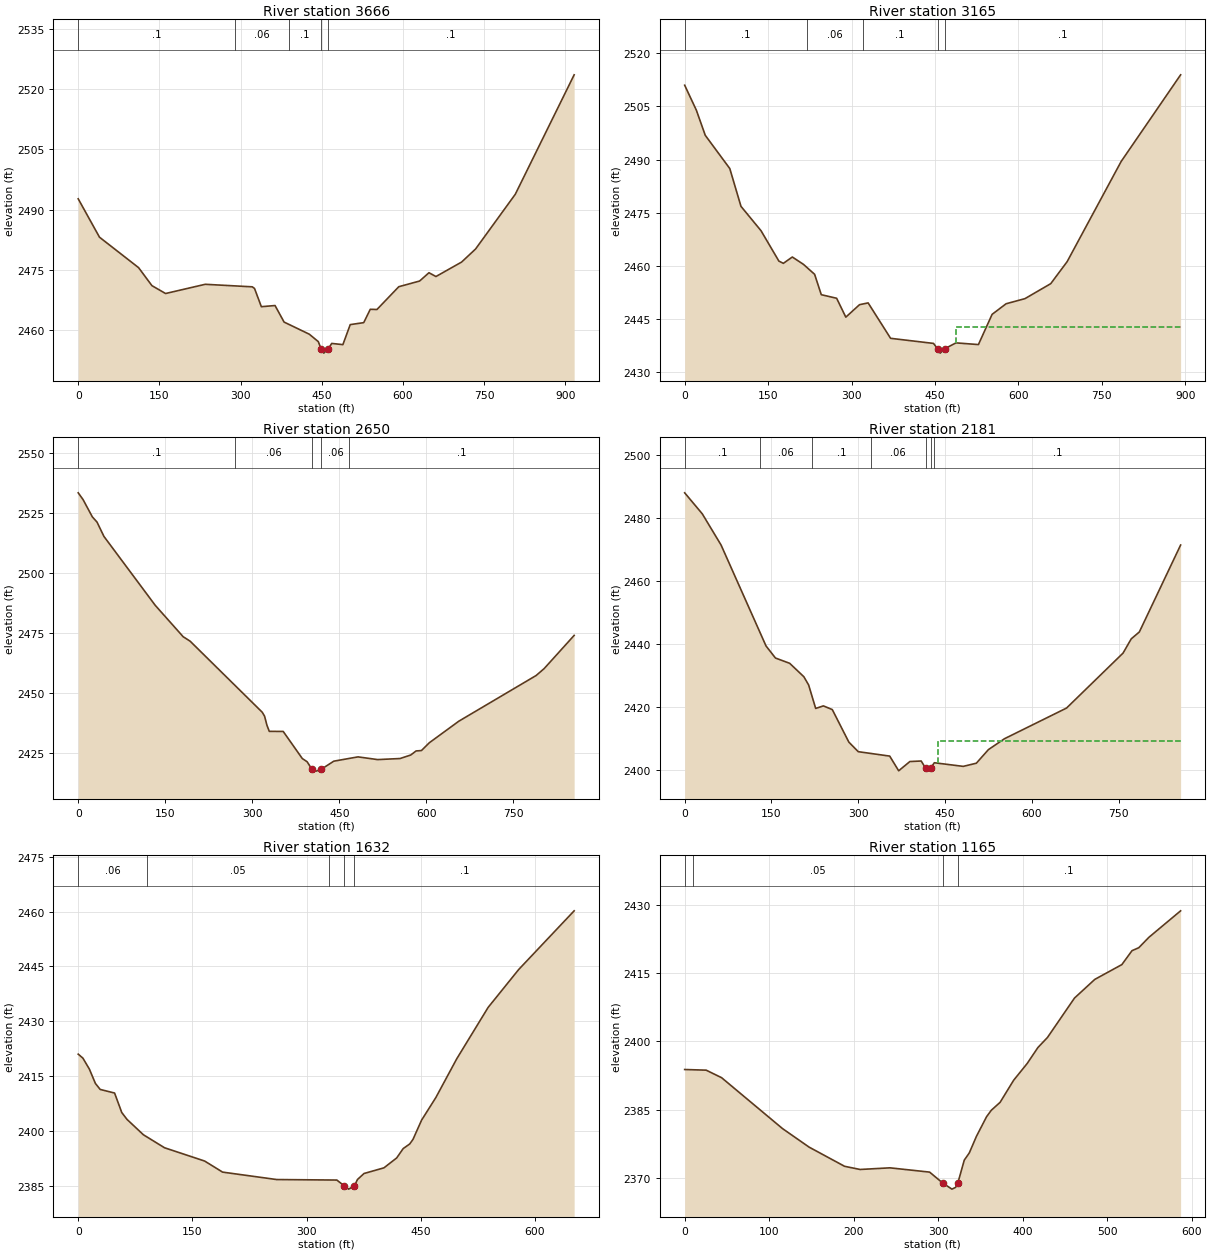
Type RM Length L Ch R = 1 ,3666    ,498.1,501.5,503.4
XS GIS Cut Line= 4
      2265909.28      682323.8532266046.13737414682739.310733972
2266061.02446738682796.519144182     2266216.219      683186.347
#Sta/Elev= 30
       0 2492.68    39.3  2483.1   111.5  2475.5   136.2    2471   161.4 2469.04
   234.6 2471.34   321.5 2470.71   325.7  2470.3   338.3 2465.75   363.6 2466.04
   380.3 2461.91   426.8 2458.89   443.5 2457.03  448.482455.264   453.7 2454.16
  461.952455.265   468.3 2456.58   488.9 2456.28   502.5 2461.28   527.4 2461.77
   539.5  2465.1   551.8 2465.05   592.2 2470.74   630.7 2472.16   647.9 2474.23
   660.8 2473.28   708.2 2476.89     734 2480.15   807.4 2493.82   916.1 2523.63
#Mann= 5 ,-1,0
       0      .1       0     290     .06       0     390      .1       0
  448.48    .045       0  461.95      .1       0
Bank Sta=448.48,461.95
XS Rating Curve= 0 ,0
Exp/Cntr=0.3,0.1

Type RM Length L Ch R = 1 ,3165    ,517.6,514.5,511
XS GIS Cut Line= 4
2265572.41942553682380.2553148952265597.91235479682723.681300016
2265563.70511455682930.1715994092265671.20176597683250.584727647
#Sta/Elev= 30
       0 2511.02      21 2503.96      37 2496.85    81.1 2487.45   101.2 2476.76
   137.3 2469.85   169.4 2461.26   177.4 2460.63   193.5 2462.42   213.5 2460.35
   233.6 2457.53   245.6 2451.76   273.2 2450.75   289.7 2445.41   314.3 2448.93
   329.8 2449.44   370.2 2439.42   447.3 2437.98  454.752436.451   459.4 2435.23
  467.272436.451   487.8 2438.13   528.1 2437.65   552.7  2446.2   577.9  2449.2
   611.7 2450.64   658.1 2454.88   687.6 2461.11   784.7 2489.45   891.6 2513.96
#Mann= 5 ,-1,0
       0      .1       0     220     .06       0     320      .1       0
  454.75    .045       0  467.27      .1       0
#XS Ineff= 2 , 0
                           487.4         2442.71
Permanent Ineff=
       F       F
Bank Sta=454.75,467.27
XS Rating Curve= 0 ,0
Exp/Cntr=0.3,0.1

Type RM Length L Ch R = 1 ,2650    ,471.8,469.2,467.6
XS GIS Cut Line= 4
2265060.57343028682428.8837659672265088.73409597682794.806811132
2265124.81487909682915.441111994 2265303.2857116683230.143929061
#Sta/Elev= 30
       0 2533.27     8.3 2530.48    24.4 2523.23    32.4 2521.08    44.4 2515.08
   132.7  2486.4   180.8 2473.32   192.9 2471.44   317.2 2441.82   321.2 2440.18
   325.3 2436.37   329.3 2433.86   353.3 2433.83   386.2 2422.53   394.5  2421.2
  402.672418.125   410.2 2417.29  419.242418.124   440.5 2421.44   482.2 2423.23
   515.9  2422.1   554.7 2422.54   573.1 2424.01   582.3  2425.7   591.5 2425.86
   605.1 2429.11   655.9 2438.09   789.2 2457.14     803 2460.02   854.7 2473.85
#Mann= 5 ,-1,0
       0      .1       0     270     .06       0  402.67    .045       0
  419.24     .06       0  467.01      .1       0
Bank Sta=402.67,419.24
XS Rating Curve= 0 ,0
Exp/Cntr=0.3,0.1

Type RM Length L Ch R = 1 ,2181    ,551.4,549.1,543.9
XS GIS Cut Line= 4
2264589.75560992682679.6145516362264651.97330213682974.631703816
2264751.78610175   683161.2942342265033.80160992683357.936006129
#Sta/Elev= 30
       0  2488.1    30.4 2481.44    62.9 2471.53   140.6 2439.48   156.9 2435.66
   181.5 2433.98     206 2429.71   214.2 2427.11   226.4 2419.66   239.7 2420.47
   255.1 2419.29   283.7 2408.97     300 2405.93   354.3 2404.53   369.8 2399.87
   389.2 2402.81   408.7 2402.97  416.35  2400.7   421.8 2399.76  425.122400.689
   431.4 2402.42   481.3 2401.27     504 2402.27   524.9 2406.59   552.7 2410.05
   659.9 2419.78   757.5 2437.22   771.7 2441.75   785.7 2443.94     857 2471.53
#Mann= 7 ,-1,0
       0      .1       0     130     .06       0     220      .1       0
  321.51     .06       0  416.35    .045       0  425.12     .06       0
  431.51      .1       0
#XS Ineff= 2 , 0
                          438.18         2409.43
Permanent Ineff=
       F       F
Bank Sta=416.35,425.12
XS Rating Curve= 0 ,0
Exp/Cntr=0.3,0.1

Type RM Length L Ch R = 1 ,1632    ,465,467.1,467.3
XS GIS Cut Line= 4
2264212.08390974683204.7785934362264391.78739225683489.258379304
2264458.16729891683514.9308904722264685.41278671683603.641109002
#Sta/Elev= 30
       0 2421.03     6.2 2419.93    14.7 2416.93    22.6 2413.02    28.9 2411.38
    47.8  2410.4    57.2 2405.08    64.1  2403.2    85.6    2399   113.4 2395.44
   166.1 2391.81   189.7 2388.78   260.7 2386.75   339.8 2386.61   349.8 2384.99
   355.3 2384.13   362.9 2385.01   366.9 2386.76   375.5  2388.4   401.7 2389.95
   418.4 2392.65     427 2395.22   435.6 2396.48   439.9 2397.74   451.1 2402.97
   469.9 2409.17   497.4 2419.78   538.6 2433.81   578.8 2444.18   651.6 2460.21
#Mann= 5 ,-1,0
       0     .06       0      90     .05       0     330      .1       0
   349.8    .045       0   362.9      .1       0
Bank Sta=349.8,362.9
XS Rating Curve= 0 ,0
Exp/Cntr=0.3,0.1

Type RM Length L Ch R = 1 ,1165    ,389.8,394.3,394.9
XS GIS Cut Line= 4
2263960.77233622683666.421205965 2264073.4821187683814.382274562
2264207.58008608683891.1427765972264453.63697018683887.216357382
#Sta/Elev= 30
       0 2393.79    25.4 2393.65    43.7 2391.99   115.7 2380.81   147.1 2376.74
   189.1 2372.52   207.5 2371.82   242.8 2372.18   289.7 2371.24  305.182368.849
   316.1  2367.5   320.5 2367.89  323.112368.847   330.7 2373.87   336.6 2375.44
   345.1 2379.11   357.1 2383.42   362.7 2384.84   373.1 2386.58   389.1 2391.43
   405.1 2395.11   417.8 2398.62   429.1 2400.83   461.1  2409.5   485.1  2413.6
   517.1 2416.85   529.1 2419.91   537.1 2420.56   549.1 2422.85   586.6 2428.67
#Mann= 4 ,-1,0
       0     .06       0      10     .05       0  305.18    .045       0
  323.11      .1       0
Bank Sta=305.18,323.11
XS Rating Curve= 0 ,0
Exp/Cntr=0.3,0.1

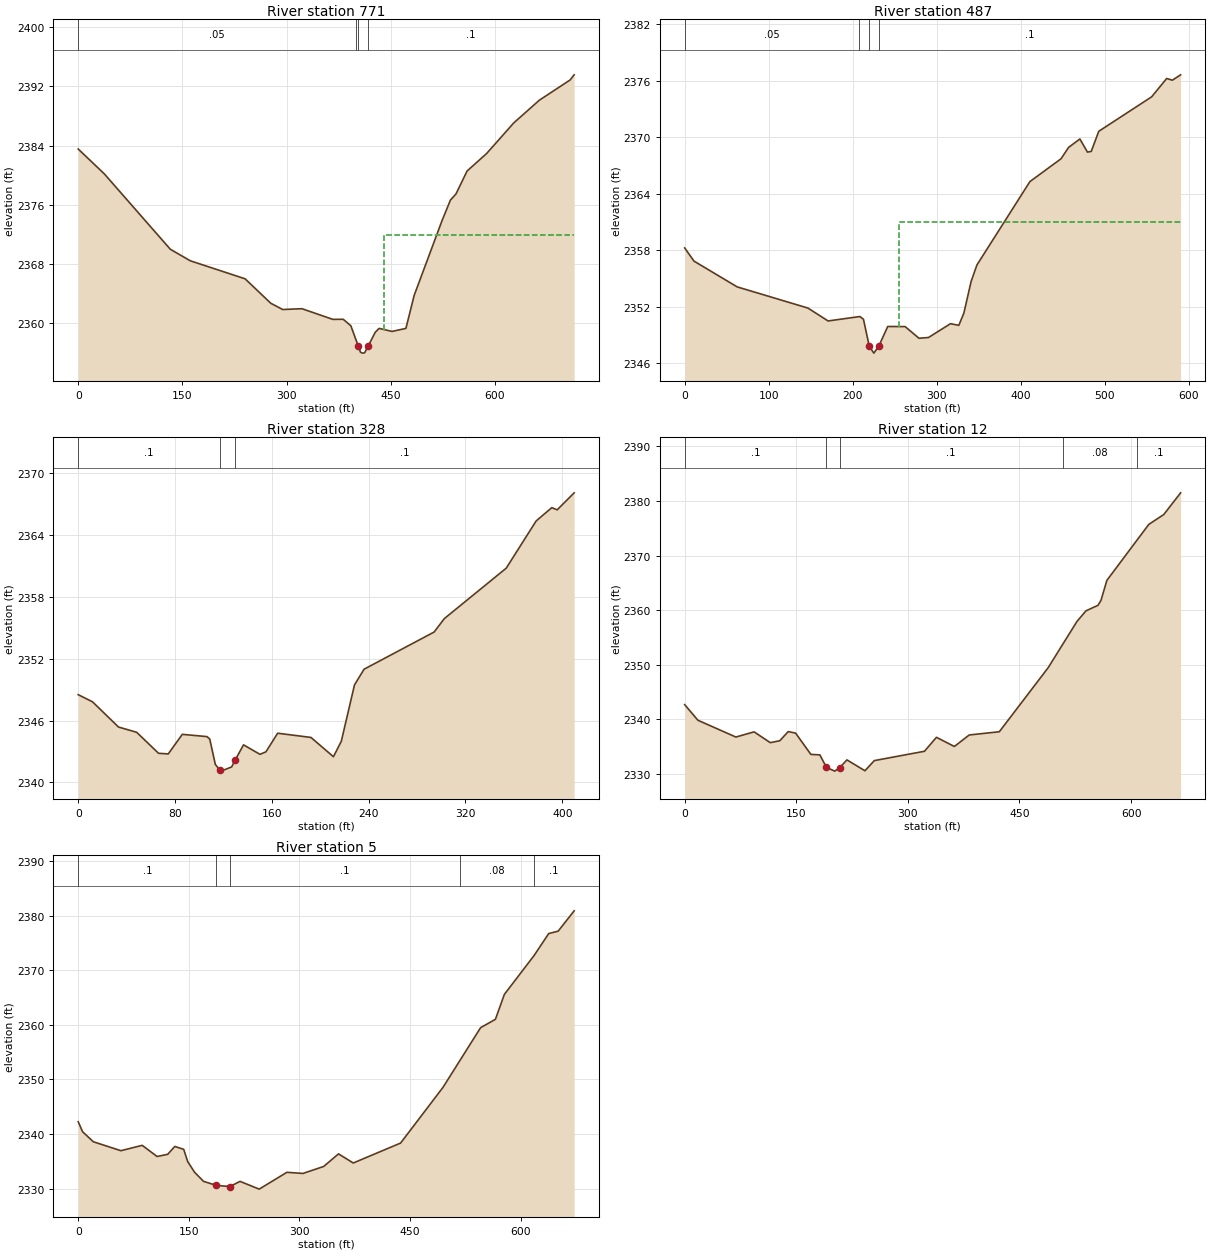
Type RM Length L Ch R = 1 ,771     ,288.4,283.4,279.6
XS GIS Cut Line= 4
2263875.94991741683848.7819318232263943.49649972684110.028073164
2264045.55118437684237.4120587152264326.06576946684224.053280564
#Sta/Elev= 30
       0 2383.53    37.6 2380.17   132.6 2369.99   161.4 2368.43   240.2    2366
   277.3 2362.69   294.4 2361.85   322.1 2361.96   366.5 2360.52   381.5 2360.53
   392.5 2359.65   403.2 2356.89   406.3 2356.09   409.2 2355.96   412.3    2356
   417.2 2356.89   427.6 2358.78   433.1  2359.3   451.7 2358.89   471.7  2359.3
   483.7 2363.78   523.7 2373.85   535.8 2376.63   543.8 2377.46   559.8 2380.56
   587.9 2382.92   626.9 2387.05   663.9 2390.13     708 2392.85   713.9 2393.55
#Mann= 4 ,-1,0
       0     .05       0  399.84      .1       0   403.2    .045       0
   417.2      .1       0
#XS Ineff= 2 , 0
                          440.72         2371.97
Permanent Ineff=
       F       F
Bank Sta=403.2,417.2
XS Rating Curve= 0 ,0
Exp/Cntr(USF)=0,0
Exp/Cntr=0.3,0.1

Type RM Length L Ch R = 1 ,487     ,157.5,158.6,161.1
XS GIS Cut Line= 4
2263888.13918491684258.8299987142263902.61634212684465.354603927
2264038.87534632684500.7792052282264254.92700353684390.786459066
#Sta/Elev= 30
       0 2358.23    11.1 2356.83    62.5 2354.09   146.7 2351.84   170.7 2350.47
   208.6 2350.94   212.8 2350.65  219.75 2347.77   225.2 2347.05  230.98 2347.78
   241.7 2349.88   262.4 2349.87   278.9 2348.63   290.2 2348.71   316.4 2350.18
   326.3    2350   332.3  2351.3   340.9 2354.65   347.8 2356.41   410.9 2365.28
     448 2367.71     457 2368.92   470.4 2369.81   479.4 2368.42   483.9 2368.49
   492.9 2370.63   555.8 2374.29   573.7 2376.24   580.5 2376.06   590.3 2376.63
#Mann= 4 ,-1,0
       0     .05       0  207.03      .1       0  219.75    .045       0
  230.98      .1       0
#XS Ineff= 2 , 0
                          255.28         2361.03
Permanent Ineff=
       F       F
Bank Sta=219.75,230.98
XS Rating Curve= 0 ,0
Exp/Cntr(USF)=0,0
Exp/Cntr=0.3,0.1

Type RM Length L Ch R = 1 ,328     ,311.4,315.8,326.9
XS GIS Cut Line= 4
2263829.89223361684528.9289167622263880.29764112684609.337543014
2264006.31115987684683.7455255162264165.32821925684739.551512392
#Sta/Elev= 30
       0 2348.52    11.8 2347.83    33.3 2345.38    48.3 2344.87    66.4 2342.83
    74.4 2342.77      86 2344.67   106.4 2344.45   108.7 2344.21   113.3 2341.75
   116.9 2341.22     118  2341.1   126.8 2341.51   129.82342.194   136.6 2343.65
   150.2 2342.73   155.1 2342.97   164.8 2344.78   192.3 2344.37   210.9  2342.5
   217.4    2344   228.3 2349.47   236.2 2350.99   294.1  2354.6   302.6 2355.91
   353.7  2360.8   378.4 2365.38   391.3 2366.67   395.8 2366.46   409.8 2368.11
#Mann= 3 ,-1,0
       0      .1       0   116.9    .045       0   129.8      .1       0
Bank Sta=116.9,129.8
XS Rating Curve= 0 ,0
Exp/Cntr(USF)=0,0
Exp/Cntr=0.3,0.1

Type RM Length L Ch R = 1 ,12      ,6.7,7.2,7.7
XS GIS Cut Line= 4
 2263847.3018459684714.4988066812263761.44495857 684838.77236177
2263776.18424638684944.6959314152264182.80888071684985.307769549
#Sta/Elev= 30
       0 2342.66    17.8  2339.8    68.8 2336.72    93.3 2337.67   115.1 2335.69
   127.8 2336.04   139.2 2337.72   149.1 2337.44   169.6 2333.54   181.7 2333.45
   190.62331.146   201.7 2330.47   208.62331.135   218.1 2332.53   242.3 2330.54
   254.9  2332.4   322.3 2334.11   338.4 2336.67   362.5 2334.99   382.5  2337.1
   422.9 2337.69   488.7 2349.46   527.3 2357.92   539.4 2359.86   555.5 2360.87
   559.5 2361.76   567.5 2365.45   623.9 2375.72   643.9 2377.51   666.6  2381.5
#Mann= 5 ,-1,0
       0      .1       0   190.6    .045       0   208.6      .1       0
  507.99     .08       0  607.99      .1       0
Bank Sta=190.6,208.6
XS Rating Curve= 0 ,0
Exp/Cntr(USF)=0,0
Exp/Cntr=0.3,0.1

Type RM Length L Ch R = 1 ,5       ,,,
XS GIS Cut Line= 4
2263839.41765142684716.1266395512263757.16115034684839.800130265
 2263765.8997944 684949.324086162264178.52507248684986.335538044
#Sta/Elev= 30
       0 2342.27       6 2340.43    20.5 2338.61    57.9 2336.97    86.8 2337.95
     107 2335.91   121.4 2336.31     131 2337.75   143.1 2337.22   148.5 2334.98
   157.9 2333.02     170 2331.36187.37532330.627205.67532330.412   219.5 2331.36
   245.5 2329.94   283.1 2333.02   304.9 2332.81     333 2334.09   353.1 2336.39
   373.1 2334.72   437.3 2338.37   494.9 2348.58   545.8 2359.48   565.9 2361.01
     578 2365.56   618.4 2372.69   638.2  2376.7     651 2377.14   672.7 2380.86
#Mann= 5 ,-1,0
       0      .1       0187.3753    .045       0205.6753      .1       0
   518.4     .08       0   618.4      .1       0
Bank Sta=187.3753,205.6753
XS Rating Curve= 0 ,0
Exp/Cntr(USF)=0,0
Exp/Cntr=0.3,0.1
LCMann Table=0

Chan Stop Cuts=-1
Use User Specified Reach Order=0
Composite Channel Slope=5